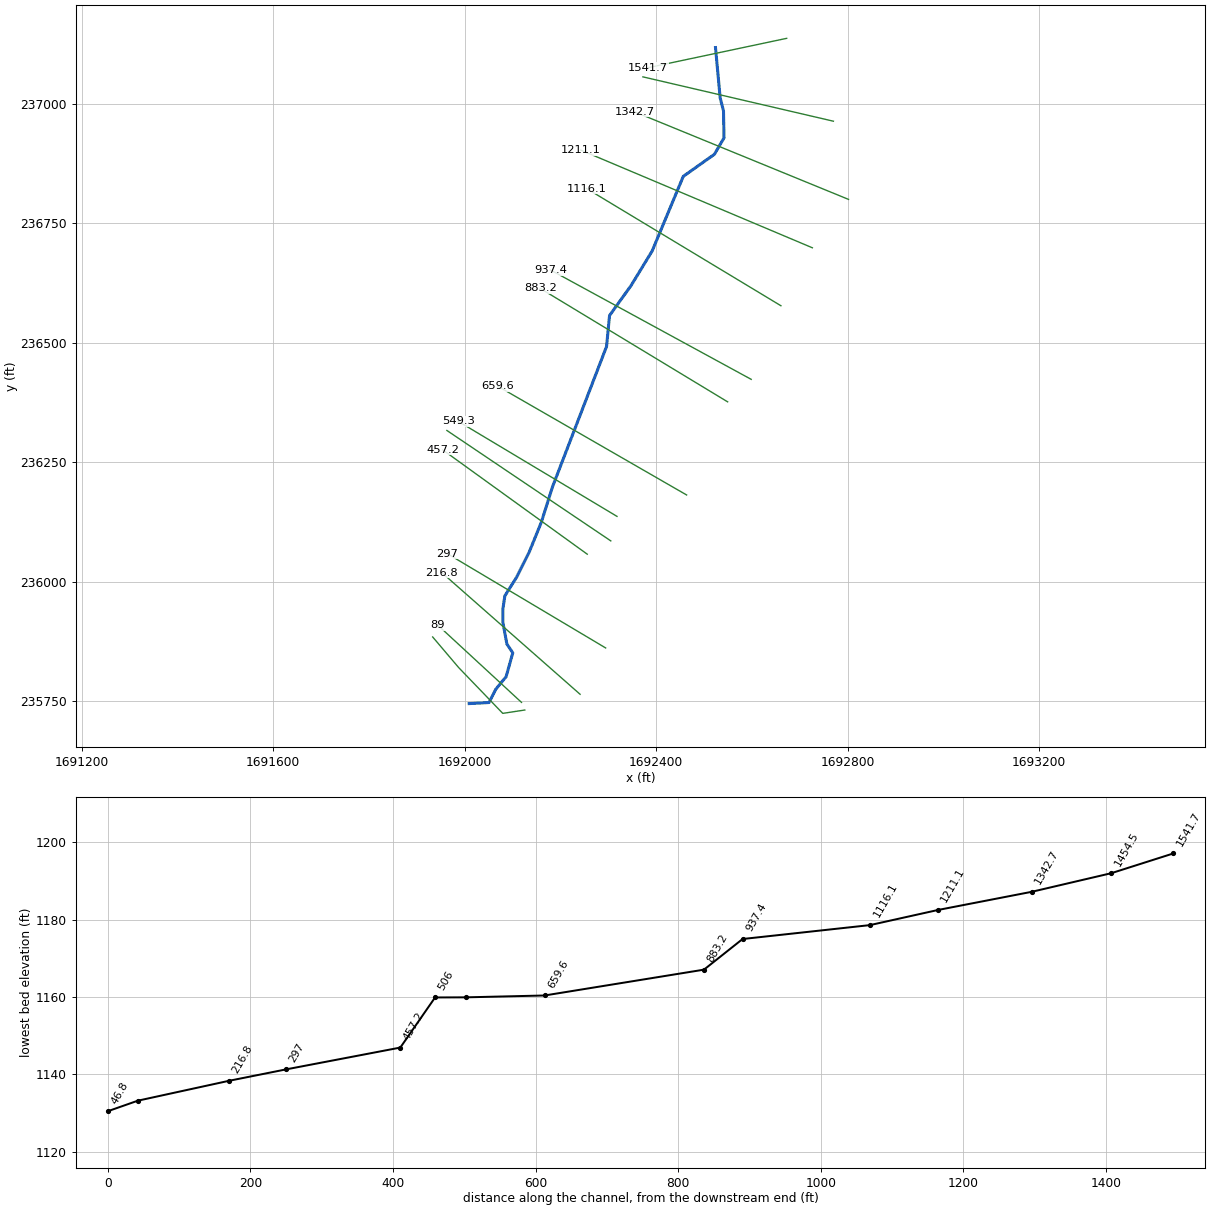
--- dnldsnbrnc.prj (project) ---

Proj Title=dnldsnbrnc
Current Plan=p01
Default Exp/Contr=0,0
English Units
Geom File=g01
Flow File=f01
Plan File=p01
BEGIN DESCRIPTION:
END DESCRIPTION:
DSS Export Rating Curves= 0
DSS Export Rating Curve Sorted= 0
DSS Export Volume Flow Curves= 0
DXF OffsetX= 0
DXF OffsetY= 0
DXF ScaleX= 0
DXF ScaleY= 0

--- dnldsnbrnc.p01 (plan) ---

Plan Title=Approximate Study - 100yr
Program Version=4.00
Geom File=g01
Flow File=f01
Subcritical Flow
K Sum by GR= 0
Std Step Tol= 0.01
Critical Tol= 0.01
Num of Std Step Trials= 20
Max Error Tol= 0.3
Flow Tol Ratio= 0.001
Split Flow NTrial= 30
Split Flow Tol= 0.02
Split Flow Ratio= 0.02
Log Output Level= 0
Friction Slope Method= 1
Unsteady Friction Slope Method= 2
Unsteady Bridges Friction Slope Method= 1
Parabolic Critical Depth
Global Vel Dist= 0 , 0 , 0
Global Log Level= 0
CheckData=True
Encroach Param=-1 ,0,0, 0
Run HTab= 0
Run UNet= 0
Run PostProcess= 0
Run WQNet= 0
UNET Theta= 0
UNET Theta Warmup= 0
UNET ZTol= 0
UNET ZSATol= 0
UNET MxIter= 0
UNET MaxInSteps= 0
UNET DtIC= 0
UNET DtMin= 0
UNET MaxCRTS= 0
UNET WFStab= 0
UNET SFStab= 0
UNET WFX= 1
UNET SFX= 1
UNET DSS MLevel= 1
UNET DZMax Abort= 0
UNET Convert EG Bridges= 0
UNET Use Existing IB Tables= 0
UNET Froude Reduction=False
UNET Froude Limit= 0
UNET Froude Power= 0
UNET Time Slicing=0,0, 5
Write IC File= 0
Echo Input=False
Echo Output=False
Write Detailed= 0
Detailed Automatic Start=False, 0
WQ ULTIMATE=-1
WQ Max Comp Step=1HOUR
WQ Output Interval=15MIN
WQ Output Selected Increments= 0
WQ Output face flow=0
WQ Output face velocity=0
WQ Output face area=0
WQ Output face dispersion=0
WQ Output cell volume=0
WQ Output cell surface area=0
WQ Output cell continuity=0
WQ Output face conc=0
WQ Output face dconc_dx=0
WQ Output face courant=0
WQ Output face peclet=0
WQ Output face adv mass=0
WQ Output face disp mass=0
WQ Output cell mass=0
WQ Output cell source sink temp=0
WQ Output cell source sink nsm=0
WQ Output MaxMinRange=-1
WQ Daily Max Min Mean=-1
WQ Daily Range=0
WQ Daily Time=0
WQ Create Restart=0
WQ Fixed Restart=0
WQ System Summary=False
Sorting and Armoring Iterations= 10
XS Update Threshold= 0.02
Hydraulics Update Threshold= 0.02
Energy Slope Method= 1
Volume Change Method= 0
XS Weighting Method= 0
Number of US Weighted Cross Sections= 1
Number of DS Weighted Cross Sections= 1
Upstream XS Weight=0.25
Main XS Weight=0.5
Downstream XS Weight=0.25
Number of DS XS's Weighted with US Boundary= 1
Upstream Boundary Weight= 1
Weight of XSs Associated with US Boundary= 0
Number of US XS's Weighted with DS Boundary= 1
Downstream Boundary Weight= 0.5
Weight of XSs Associated with DS Boundary= 0.5
Sediment Output Level= 4
Mass or Volume Output= 0
Output Increment Type= 1
Profile and TS Output Increment= 10
XS Output Flag= 0
XS Output Increment= 10
Disregard all LS=0
Disregard all Conn=0
Disregard all Breaches=0
Disregard all Pumps=0

--- dnldsnbrnc.f01 (steady flow) ---

Flow Title=USGS Regression Equation
Program Version=4.00
Number of Profiles= 1
Profile Names=P100yr
River Rch & RM=dnldsnbrnc,Main            ,1541.7
     363
River Rch & RM=dnldsnbrnc,Main            ,297
     381
Boundary for River Rch & Prof#=dnldsnbrnc,Main            , 1
Up Type= 0
Dn Type= 3
Dn Slope=0.021228
DSS Import GetInterval= 0
DSS Import GetPeak= 0
DSS Import FillOption= 0

--- dnldsnbrnc.g01 (geometry) ---

Geom Title=USGS 3m DEM
Program Version=4.00

River Reach=dnldsnbrnc      ,Main
Reach XY= 24
      1692524.11       237117.76     1692533.914      237012.128
     1692540.824      236985.503     1692541.891      236928.781
     1692521.775      236894.288     1692456.811      236848.184
     1692391.847      236692.062      1692347.84      236619.764
     1692302.784      236556.896     1692296.498      236491.932
     1692183.335      236197.501     1692160.284      236124.155
      1692134.89      236061.553     1692108.574      236008.959
     1692084.075      235970.025     1692079.837      235941.772
     1692079.837      235914.932     1692088.313      235869.021
     1692100.633      235850.675     1692086.523      235800.351
     1692079.399      235792.061     1692065.141      235774.505
     1692050.972      235746.693     1692009.498      235744.454

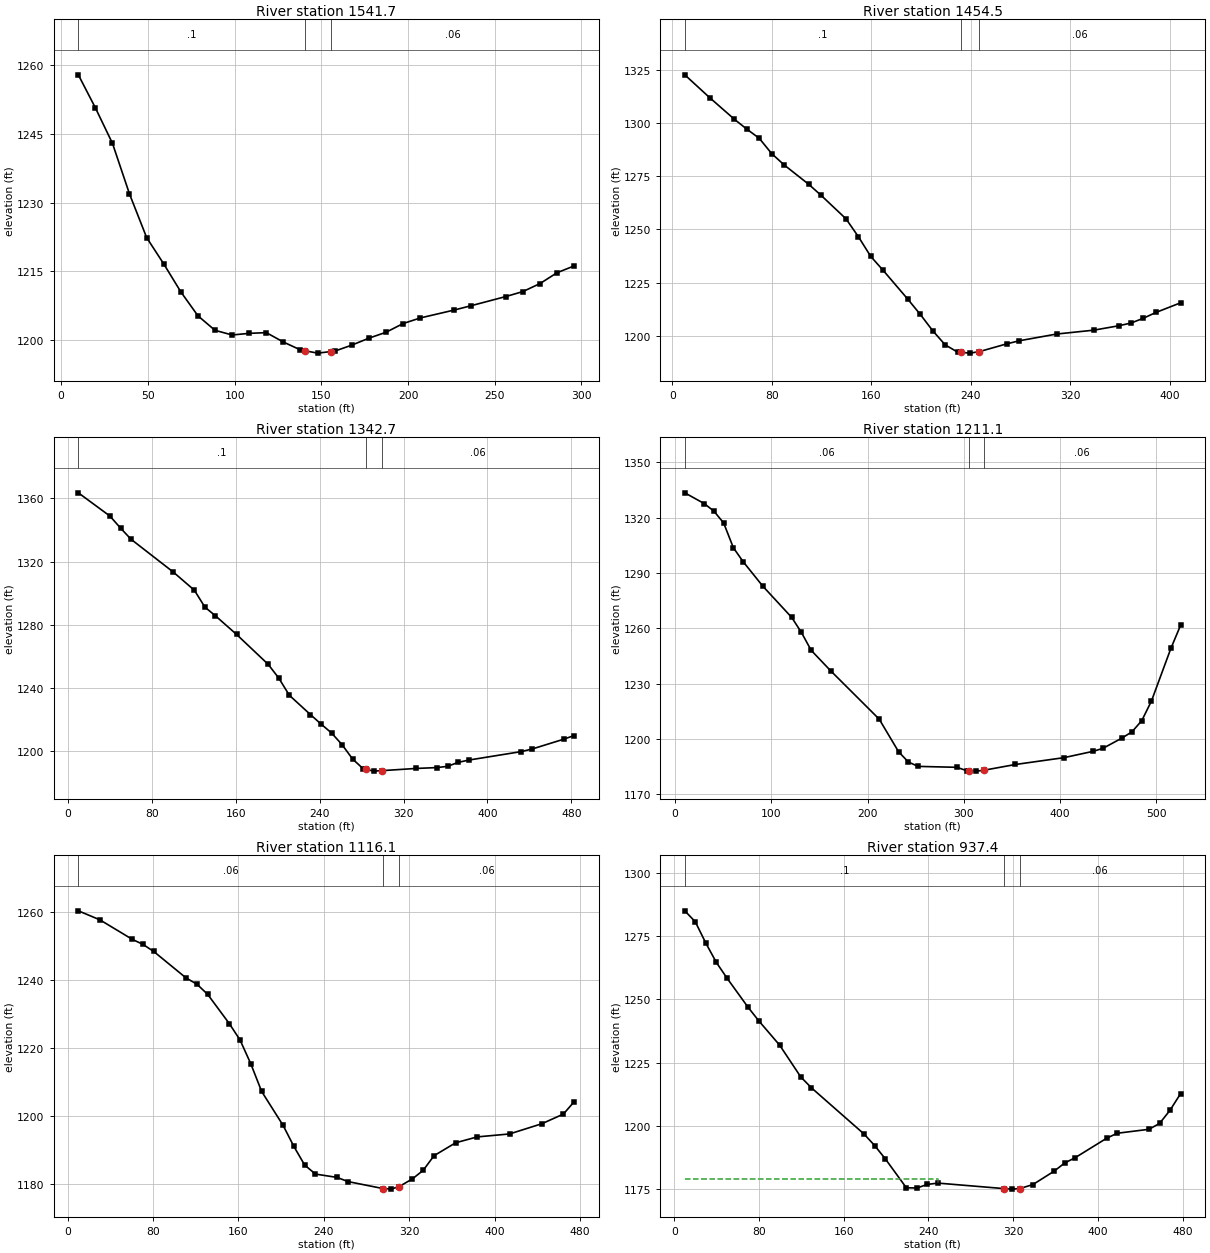
Type RM Length L Ch R = 1 ,1541.7  ,97.5,87.2,77.1
XS GIS Cut Line= 2
     1692672.871      237137.129     1692383.509      237075.706
#Sta/Elev= 30
     9.9 1257.88    19.7  1250.7    29.6 1242.91    39.4 1231.88    49.3 1222.35
    59.2 1216.58      69 1210.51    78.9 1205.27    88.7 1202.12    98.6  1201.1
   108.5 1201.46   118.3 1201.61   128.2 1199.55     138 1197.84   140.4 1197.67
   147.9 1197.14   155.4 1197.47   157.8 1197.58   167.6 1198.89   177.5 1200.41
   187.3 1201.69   197.2  1203.6   207.1 1204.82   226.8 1206.56   236.6 1207.51
   256.4 1209.49   266.2 1210.57   276.1 1212.32   285.9 1214.68   295.8 1216.18
#Mann= 3 , 0 , 0
     9.9      .1       0   140.4    .045       0   155.4     .06       0
Bank Sta=140.4,155.4
XS Rating Curve= 0 ,0
Exp/Cntr=0.3,0.1

Type RM Length L Ch R = 1 ,1454.5  ,115.2,111.7,108.1
XS GIS Cut Line= 2
     1692770.482      236963.645     1692372.441      237056.474
#Sta/Elev= 30
      10 1322.51    29.9 1311.86    49.8 1301.71    59.8 1297.07    69.8 1292.79
    79.8 1285.62    89.7 1280.35   109.7 1271.15   119.6    1266   139.6 1255.01
   149.5 1246.69   159.5 1237.38   169.5 1230.83   189.4 1217.26   199.4 1210.14
   209.3 1202.57   219.3 1195.94   229.3 1192.51   231.8 1192.39   239.3 1192.02
   246.8 1192.72   269.2 1196.42   279.1 1197.83     309 1200.97   338.9 1202.79
   358.9 1204.84   368.8 1206.13   378.8 1208.39   388.8 1211.08   408.7 1215.62
#Mann= 3 , 0 , 0
      10      .1       0   231.8    .045       0   246.8     .06       0
Bank Sta=231.8,246.8
XS Rating Curve= 0 ,0
Exp/Cntr=0.3,0.1

Type RM Length L Ch R = 1 ,1342.7  ,131.7,131.7,131.6
XS GIS Cut Line= 2
     1692802.058      236799.978     1692355.514      236983.125
#Sta/Elev= 30
    10.1 1363.57    40.2 1348.85    50.3 1341.24    60.3 1334.15   100.6 1313.35
   120.7 1301.83   130.7 1291.13   140.8 1285.61   160.9 1273.82     191 1254.89
   201.1 1246.17   211.2 1235.25   231.3 1223.02   241.3 1217.09   251.4 1211.38
   261.4 1203.98   271.5 1194.84   281.5 1188.73   284.1 1188.34   291.6  1187.2
   299.1 1187.49   331.8 1188.89   351.9 1189.45     362 1190.24     372 1192.74
   382.1  1194.2   432.4  1199.6   442.4 1201.19   472.6 1207.42   482.6 1209.77
#Mann= 3 , 0 , 0
    10.1      .1       0   284.1    .045       0   299.1     .06       0
Bank Sta=284.1,299.1
XS Rating Curve= 0 ,0
Exp/Cntr=0.3,0.1

Type RM Length L Ch R = 1 ,1211.1  ,98.3,95,91.7
XS GIS Cut Line= 2
     1692726.492      236698.662     1692242.669      236903.193
#Sta/Elev= 30
    10.1 1333.53    30.3 1327.69    40.4 1323.57    50.5 1317.14    60.6 1303.69
    70.7 1296.18    90.9 1283.03   121.2  1265.9   131.3 1257.73   141.4 1248.06
   161.6 1236.98   212.1  1210.7   232.3 1192.96   242.4 1187.45   252.5 1185.06
   292.9 1184.56     303 1182.72   305.6 1182.66   313.1 1182.49   320.6 1182.94
   353.6 1186.09   404.1  1189.8   434.4 1193.24   444.5 1194.83   464.7 1200.54
   474.8 1203.85   484.9 1209.86     495 1220.56   515.2 1249.13   525.3  1261.7
#Mann= 3 , 0 , 0
    10.1     .06       0   305.6    .045       0   320.6     .06       0
Bank Sta=305.6,320.6
XS Rating Curve= 0 ,0
Exp/Cntr=0.3,0.1

Type RM Length L Ch R = 1 ,1116.1  ,177.7,178.7,179.7
XS GIS Cut Line= 2
     1692660.781       236577.36     1692254.816      236822.683
#Sta/Elev= 30
    10.1  1260.4    30.3 1257.75    60.6 1252.02    70.6 1250.53    80.7 1248.45
     111 1240.66   121.1 1238.84   131.2 1235.84   151.4 1227.26   161.5 1222.43
   171.6 1215.41   181.7 1207.31   201.8 1197.33   211.9 1191.13     222 1185.67
   232.1 1183.01   252.3 1182.04   262.4 1180.82   295.3 1178.76   302.8 1178.59
   310.3 1179.31   322.9 1181.61     333 1184.13   343.1 1188.41   363.3 1192.21
   383.5 1193.94   413.8 1194.81   444.1 1197.82   464.2 1200.65   474.3 1204.28
#Mann= 3 , 0 , 0
    10.1     .06       0   295.3    .045       0   310.3     .06       0
Bank Sta=295.3,310.3
XS Rating Curve= 0 ,0
Exp/Cntr=0.3,0.1

Type RM Length L Ch R = 1 ,937.4   ,55.7,54.2,52.7
XS GIS Cut Line= 2
     1692598.705       236423.24     1692179.157       236652.28
#Sta/Elev= 30
      10    1285    19.9 1280.67    29.9  1272.2    39.8 1264.59    49.8 1258.42
    69.7 1246.89    79.7 1241.58    99.6 1231.86   119.5 1219.32   129.5 1215.05
   179.2 1196.77   189.2 1192.21   199.2 1186.99   219.1 1175.53     229 1175.43
     239 1176.86     249 1177.37   311.2  1175.2   318.7 1174.99   326.2 1175.21
   338.6  1176.8   358.5 1182.06   368.5  1185.3   378.4  1187.4   408.3 1195.14
   418.2 1197.08   448.1 1198.64   458.1 1200.95     468 1206.17     478 1212.75
#Mann= 3 , 0 , 0
      10      .1       0   311.2    .045       0   326.2     .06       0
#XS Ineff= 2 , 0
       0     249    1179               0
Permanent Ineff=
       F       F
Bank Sta=311.2,326.2
XS Rating Curve= 0 ,0
Exp/Cntr=0.3,0.1

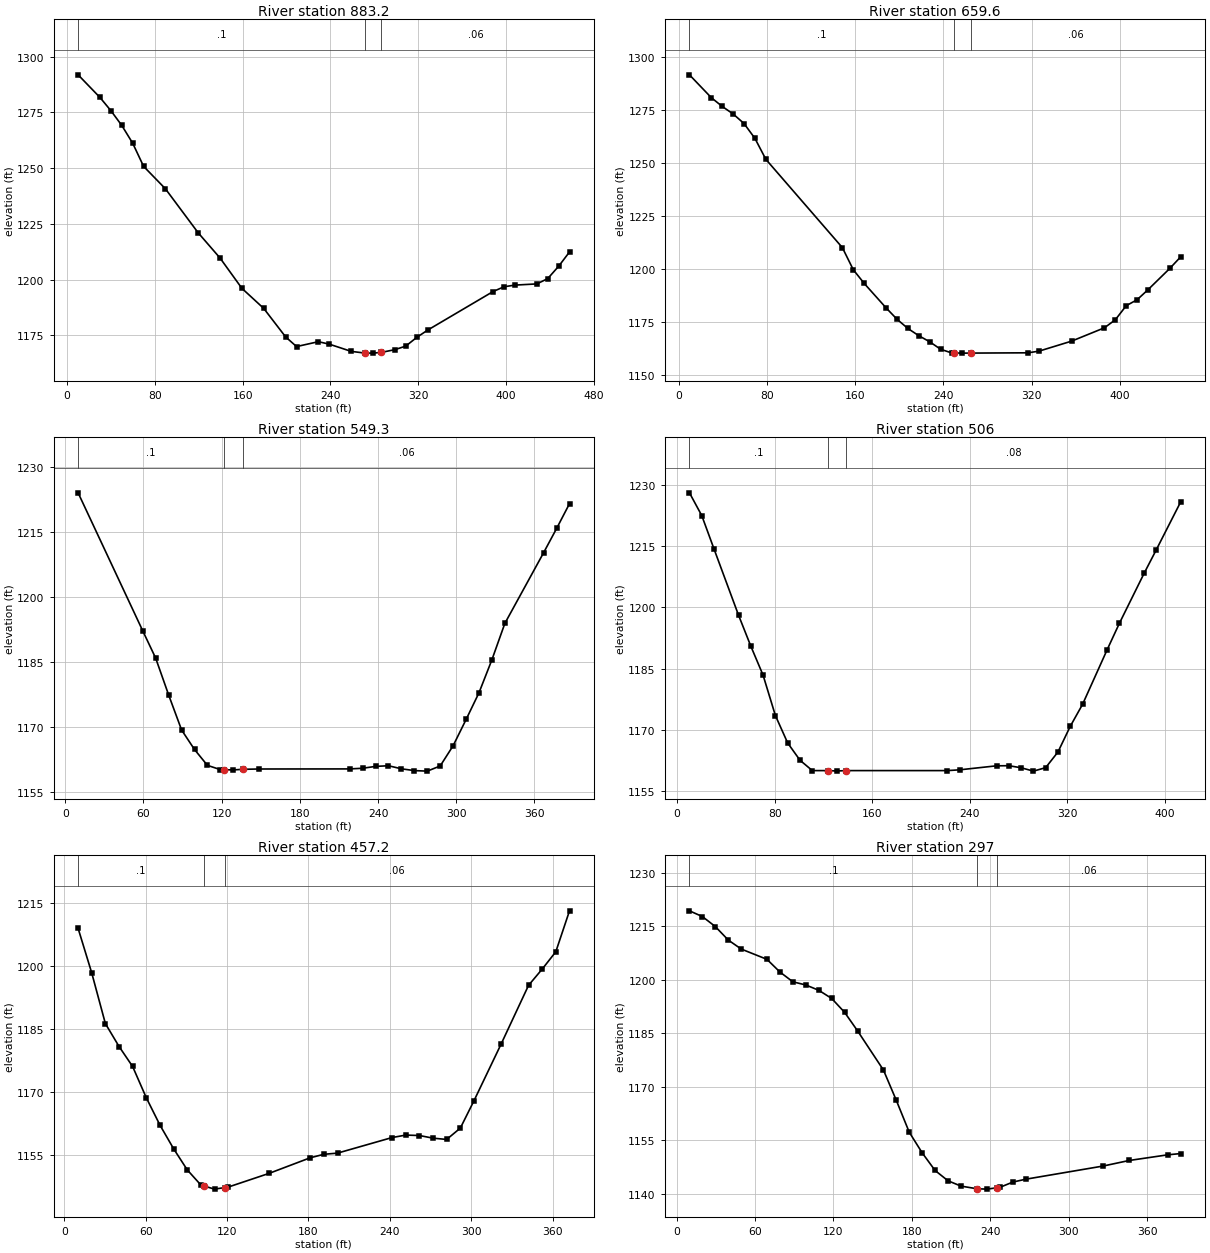
Type RM Length L Ch R = 1 ,883.2   ,222.4,223.5,224.7
XS GIS Cut Line= 2
     1692549.473      236376.148     1692157.751       236613.75
#Sta/Elev= 30
      10 1291.88    29.9 1281.75    39.8 1275.86    49.8  1269.2    59.8 1261.18
    69.7 1250.84    89.6 1240.77   119.5 1221.02   139.4 1209.73   159.4  1196.1
   179.3  1187.1   199.2 1174.35   209.2    1170   229.1 1172.19     239 1171.09
     259 1167.85   271.4 1167.09   278.9 1167.06   286.4 1167.38   298.8 1168.61
   308.8 1170.21   318.7 1174.08   328.7 1177.37   388.4 1194.68   398.4 1196.83
   408.3 1197.57   428.3  1198.1   438.2 1200.47   448.2 1206.02   458.1 1212.43
#Mann= 3 , 0 , 0
      10      .1       0   271.4    .045       0   286.4     .06       0
Bank Sta=271.4,286.4
XS Rating Curve= 0 ,0
Exp/Cntr=0.3,0.1

Type RM Length L Ch R = 1 ,659.6   ,110.7,110.3,109.9
XS GIS Cut Line= 3
     1692463.791      236181.194      1692266.75      236294.909
     1692069.709      236408.624
#Sta/Elev= 30
     9.9 1291.76    29.7 1280.98    39.6 1276.83    49.5 1273.27    59.3 1268.78
    69.2 1261.76    79.1 1251.87   148.4 1210.19   158.3 1199.75   168.2 1193.28
   187.9  1181.8   197.8 1176.43   207.7 1172.04   217.6 1168.62   227.5 1165.74
   237.4 1162.21   247.3 1160.49   249.7 1160.47   257.2 1160.38   264.7  1160.4
   316.5 1160.53   326.4  1161.3   356.1 1166.05   385.8 1172.34   395.7 1176.15
   405.5 1182.76   415.4 1185.59   425.3 1190.34   445.1 1200.42     455 1205.92
#Mann= 3 , 0 , 0
     9.9      .1       0   249.7    .045       0   264.7     .06       0
Bank Sta=249.7,264.7
XS Rating Curve= 0 ,0
Exp/Cntr=0.3,0.1

Type RM Length L Ch R = 1 ,549.3   ,44.6,43.3,41.9
XS GIS Cut Line= 2
     1692318.293      236136.406     1691986.507      236335.478
#Sta/Elev= 28
     9.9 1223.97    59.5 1192.19    69.4 1185.92    79.4  1177.4    89.3 1169.37
    99.2 1164.88   109.1 1161.23   119.1 1160.24   121.5 1160.22     129 1160.18
   136.5 1160.32   148.8 1160.39   218.3 1160.41   228.2 1160.56   238.1 1160.99
     248 1161.14     258 1160.43   267.9 1160.02   277.8  1159.9   287.7 1161.09
   297.6 1165.74   307.6 1171.81   317.5 1177.97   327.4 1185.56   337.3 1193.91
   367.1 1210.22     377 1215.76   386.9 1221.47
#Mann= 3 , 0 , 0
     9.9      .1       0   121.5    .045       0   136.5     .06       0
#XS Ineff= 2 , 0
       0                     248       0
Permanent Ineff=
       F       F
Bank Sta=121.5,136.5
XS Rating Curve= 0 ,0
Exp/Cntr=0.3,0.1

Type RM Length L Ch R = 1 ,506     ,49.5,48.8,48
XS GIS Cut Line= 2
     1692305.449      236085.033     1691962.961      236316.213
#Sta/Elev= 28
    10.1 1228.02    20.2 1222.45    30.2 1214.31    50.4 1198.03    60.5 1190.43
    70.5 1183.36    80.6 1173.48    90.7 1166.75   100.8 1162.53   110.9    1160
   123.5    1160     131  1159.9   138.5    1160   221.7    1160   231.8 1160.19
     262 1161.17   272.1  1161.2   282.2 1160.69   292.3 1159.87   302.3 1160.72
   312.4 1164.56   322.5 1170.85   332.6 1176.24   352.7 1189.57   362.8 1196.08
     383 1208.27   393.1  1214.1   413.2 1225.88
#Mann= 3 , 0 , 0
    10.1      .1       0   123.5    .045       0   138.5     .08       0
#XS Ineff= 2 , 0
       0                     231       0
Permanent Ineff=
       F       F
Bank Sta=123.5,138.5
XS Rating Curve= 0 ,0
Exp/Cntr=0.3,0.1

Type RM Length L Ch R = 1 ,457.2   ,158.1,160.2,162.5
XS GIS Cut Line= 2
     1692256.217      236057.205     1691954.398      236275.542
#Sta/Elev= 30
    10.1 1209.05    20.1 1198.48    30.2 1186.36    40.3 1180.89    50.3 1176.13
    60.4 1168.67    70.5 1162.13    80.5 1156.54    90.6 1151.49   100.7 1147.86
   103.2 1147.62   110.7  1146.9   118.2 1147.27   120.8 1147.39     151 1150.66
   181.2 1154.36   191.3  1155.2   201.4 1155.48   241.6 1159.19   251.7 1159.78
   261.8 1159.68   271.8 1159.05   281.9 1158.74     292 1161.45     302 1167.93
   322.2 1181.57   342.3 1195.47   352.4 1199.36   362.4 1203.47   372.5 1213.23
#Mann= 3 , 0 , 0
    10.1      .1       0   103.2    .045       0   118.2     .06       0
Bank Sta=103.2,118.2
XS Rating Curve= 0 ,0
Exp/Cntr=0.3,0.1

Type RM Length L Ch R = 1 ,297     ,92.5,80.2,70.8
XS GIS Cut Line= 2
     1692294.633      235860.956     1691963.369      236058.616
#Sta/Elev= 30
     9.9 1219.32    19.8 1217.71    29.7  1214.9    39.6 1211.12    49.5  1208.6
    69.2 1205.71    79.1 1202.16      89 1199.41    98.9 1198.52   108.8 1197.04
   118.7 1194.74   128.6 1190.84   138.5 1185.65   158.3 1174.66   168.1  1166.2
     178 1157.25   187.9 1151.45   197.8 1146.49   207.7  1143.6   217.6 1142.11
   229.9 1141.36   237.4 1141.26   244.9 1141.63   247.3 1141.75   257.2 1143.23
   267.1 1144.04   326.4 1147.74   346.2 1149.29   375.9 1150.89   385.8 1151.24
#Mann= 3 , 0 , 0
     9.9      .1       0   229.9    .045       0   244.9     .06       0
Bank Sta=229.9,244.9
XS Rating Curve= 0 ,0
Exp/Cntr=0.3,0.1

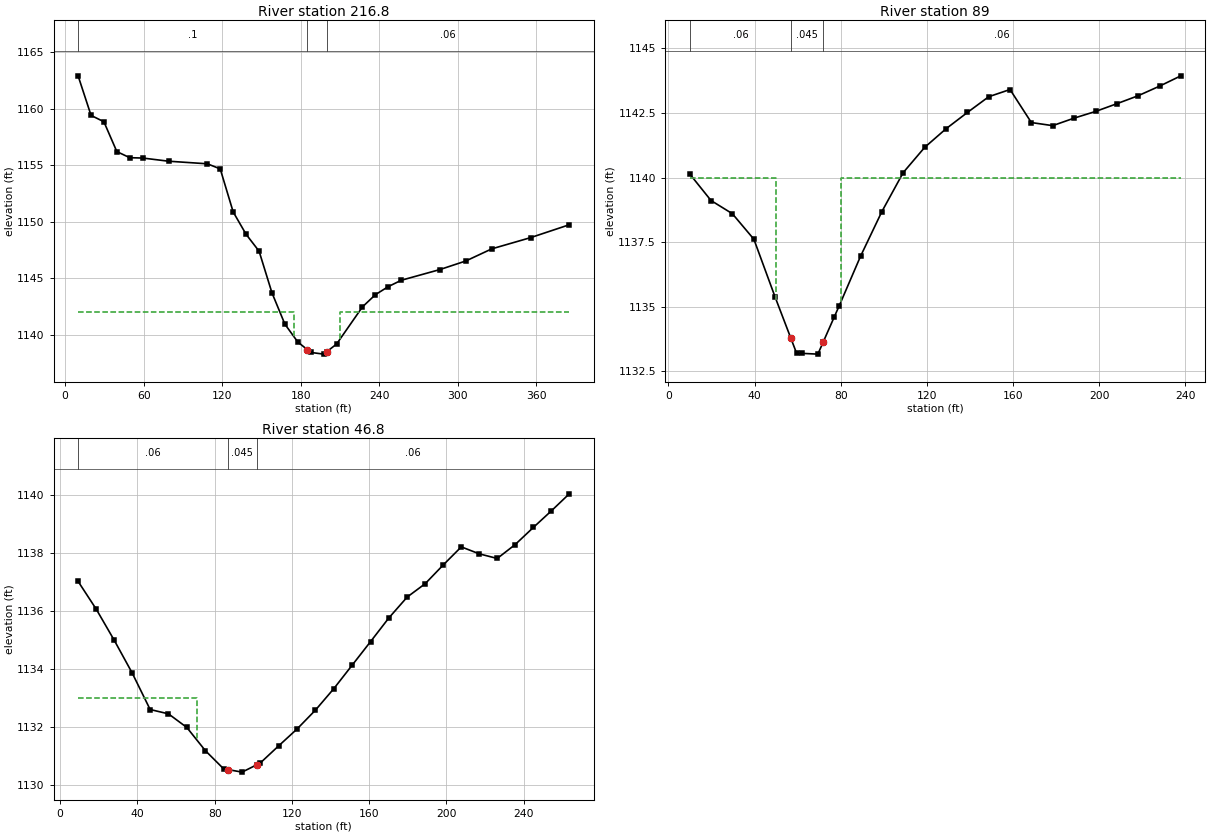
Type RM Length L Ch R = 1 ,216.8   ,121.3,127.7,131.3
XS GIS Cut Line= 2
     1692241.233       235763.95     1691952.258      236018.676
#Sta/Elev= 29
     9.9 1162.91    19.8 1159.41    29.6 1158.85    39.5 1156.21    49.4 1155.67
    59.3 1155.64      79 1155.36   108.7 1155.13   118.5 1154.68   128.4 1150.87
   138.3 1148.89   148.2  1147.4     158 1143.73   167.9 1140.95   177.8 1139.37
     1851138.701   187.7 1138.45   197.5  1138.3     2001138.523   207.4 1139.19
   227.2 1142.48   237.1 1143.56   246.9 1144.27   256.8 1144.83   286.4 1145.78
   306.2 1146.54     326 1147.61   355.6  1148.6   385.2 1149.74
#Mann= 3 , 0 , 0
     9.9      .1       0     185    .045       0     200     .06       0
#XS Ineff= 2 , 0
       0     175    1142     210       0    1142
Permanent Ineff=
       F       F
Bank Sta=185,200
XS Rating Curve= 0 ,0
Exp/Cntr=0.3,0.1

Type RM Length L Ch R = 1 ,89      ,43.8,42.2,40.6
XS GIS Cut Line= 2
     1692118.811      235746.996     1691944.152      235908.541
#Sta/Elev= 28
     9.9 1140.14    19.8 1139.11    29.7  1138.6    39.7 1137.61    49.6 1135.36
    56.91133.767    59.5  1133.2    61.9 1133.19    69.4 1133.16    71.91133.633
    76.9 1134.58    79.3 1135.03    89.2 1136.95    99.1 1138.68     109 1140.19
     119 1141.17   128.9 1141.89   138.8 1142.52   148.7 1143.13   158.6 1143.41
   168.5 1142.13   178.4 1142.01   188.3  1142.3   198.3 1142.56   208.2 1142.86
   218.1 1143.17     228 1143.54   237.9 1143.94
#Mann= 3 , 0 , 0
     9.9     .06       0    56.9    .045       0    71.9     .06       0
#XS Ineff= 2 , 0
       0      50    1140      80       0    1140
Permanent Ineff=
       F       F
Bank Sta=56.9,71.9
XS Rating Curve= 0 ,0
Exp/Cntr=0.3,0.1

Type RM Length L Ch R = 1 ,46.8    ,64.3,46.8,28.7
XS GIS Cut Line= 4
     1692125.765      235731.028     1692079.669      235723.978
     1691987.478      235819.966     1691933.248      235883.957
#Sta/Elev= 30
     9.3 1137.01    18.7 1136.05      28 1134.98    37.3 1133.85    46.6 1132.59
    56.1 1132.44    65.6 1131.97    75.2 1131.17    84.7 1130.54    86.7 1130.52
    94.2 1130.43   101.7 1130.68   103.7 1130.75   113.2 1131.34   122.7 1131.92
   132.2 1132.57   141.7 1133.31   151.2 1134.12   160.7 1134.93   170.2 1135.75
   179.7 1136.47     189 1136.93   198.4 1137.58   207.7  1138.2     217 1137.96
   226.3  1137.8   235.6 1138.28     245 1138.87   254.3 1139.44   263.6 1140.03
#Mann= 3 , 0 , 0
     9.3     .06       0    86.7    .045       0   101.7     .06       0
#XS Ineff= 2 , 0
       0      71    1133               0
Permanent Ineff=
       F       F
Bank Sta=86.7,101.7
XS Rating Curve= 0 ,0
Exp/Cntr=0.3,0.1

Chan Stop Cuts=-1
Use User Specified Reach Order=0